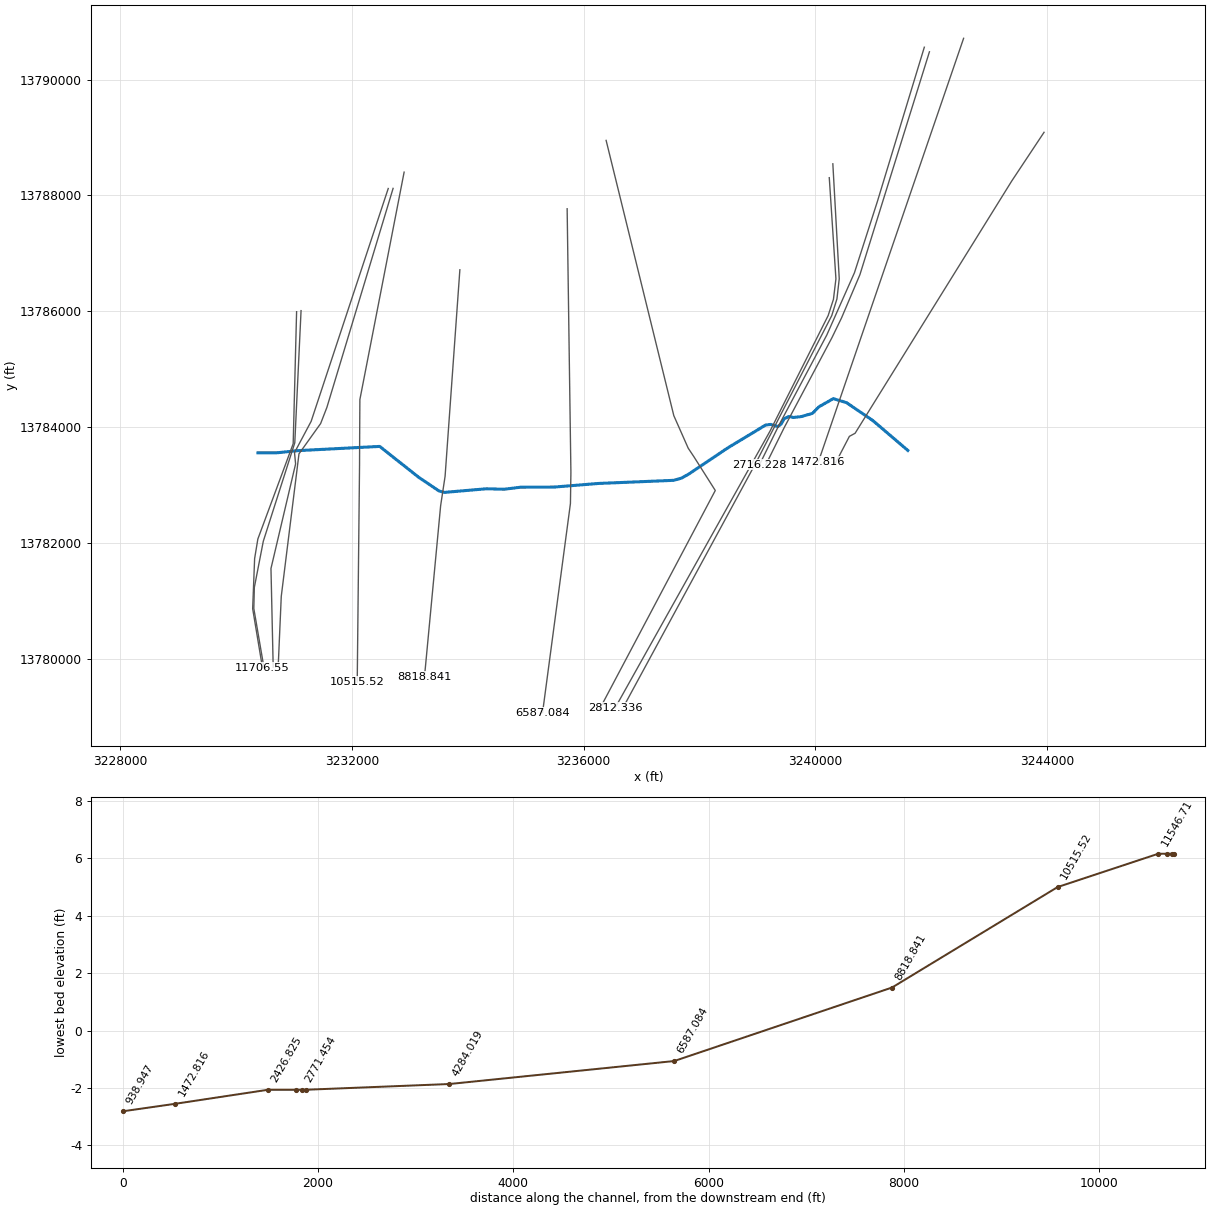
--- F220-00-00.prj (project) ---

Proj Title=F220-00-00
Current Plan=p09
Default Exp/Contr=.3,.1
English Units
Geom File=g01
Geom File=g02
Flow File=f05
Flow File=f04
Plan File=p08
Plan File=p09
Y Axis Title=Elevation
X Axis Title(PF)=Main Channel Distance
X Axis Title(XS)=Station
BEGIN DESCRIPTION:
Galveston Bay
Pine Gully
HCFCD Unit F220-00-00
Flood Hazard Model
10, 2, 1, 0.2% Event
Filename F220_00_00.prj
Prepared by: Tim Gilboy   Date: 2/20/04
Reviewed by:
STATUS FINAL
END DESCRIPTION:
DSS Export Rating Curves= 0
DSS Export Rating Curve Sorted= 0
DSS Export Volume Flow Curves= 0
DXF OffsetX= 0
DXF OffsetY= 0
DXF ScaleX= 1
DXF ScaleY= 10

--- F220-00-00.p09 (plan) ---

Plan Title=Floodway
Version=Version 3.0.1  Mar 2001
Short Identifier=Floodway0607
Geom File=g02
Flow File=f05
Subcritical Flow
K Sum by GR= 0
Std Step Tol= 0.01
Critical Tol= 0.01
Num of Std Step Trials= 20
Max Error Tol= 0.3
Flow Tol Ratio= 0.001
Split Flow NTrial= 30
Split Flow Tol= 0.02
Split Flow Ratio= 0.02
Log Output Level= 0
Friction Slope Method= 0
Unsteady Friction Slope Method= 2
Secant Critical Depth
Global Vel Dist= 0 , 0 , 0
Global Log Level= 0
CheckData=True
Encroach Param=-1 ,0,0, 2
Encroach River=F220-00-00
Encroach Reach=F220-00-00_0009
Encroach Node=11706.55
       1  4877.1  5020.9
Encroach Node=11686.01
       1    4800    5080
Encroach Node=11662
       1    4800  5020.9
Encroach Node=11638.41
       1    4800  5020.9
Encroach Node=11546.71
       1    4800  5020.9
Encroach Node=10515.52
       1    4900    5080
Encroach Node=8818.841
       1 4947.61    5049
Encroach Node=6587.084
       1    4942 5047.83
Encroach Node=4284.019
       1    4949 5040.65
Encroach Node=2812.336
       1    4961 5041.09
Encroach Node=2771.454
       1 4956.28 5023.72
Encroach Node=2741
       1    4800    5075
Encroach Node=2716.228
       1 4956.28 5023.72
Encroach Node=2426.825
       1    4940 5038.72
Encroach Node=1472.816
       1    4864    5100
Encroach Node=938.947
       1    4861    5099
Computation Interval=1HOUR
Output Interval=1HOUR
Run HTab= 0
Run UNet= 0
Run PostProcess= 0
UNET Theta= 1
UNET ZTol= 0.02
UNET ZSATol= 0.1
UNET MxIter= 20
UNET MaxInSteps= 20
UNET DtIC= 0
UNET DtMin= 0
UNET MaxCRTS= 20
UNET WFStab= 2
UNET SFStab= 1
UNET WFX= 1
UNET SFX= 1
UNET Convert EG Bridges=-1
UNET Use Existing IB Tables=-1
Instantaneous Interval=1HOUR
Write IC File= 0
Write Velocity= 0
Write Detailed= 0

--- F220-00-00.p08 (plan) ---

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Plan Title=FEMA Effective June 2007
Short Identifier=FEMAeff0607
Geom File=g01
Flow File=f04

--- F220-00-00.f05 (steady flow) ---

Flow Title=Floodway
Version=Version 3.0.1  Mar 2001
Number of Profiles= 2
Profile Names=1PCT_100yr, 1PCTFloodway_100yrFW
River Rch & RM=F220-00-00,F220-00-00_0009            ,11706.55
     260     260
River Rch & RM=F220-00-00,F220-00-00_0009            ,11638.41
     267     267
River Rch & RM=F220-00-00,F220-00-00_0009            ,11546.71
     367     367
River Rch & RM=F220-00-00,F220-00-00_0009            ,10515.52
     621     621
River Rch & RM=F220-00-00,F220-00-00_0009            ,8818.841
     856     856
River Rch & RM=F220-00-00,F220-00-00_0009            ,6587.084
    1193    1193
River Rch & RM=F220-00-00,F220-00-00_0009            ,4284.019
    2016    2016
River Rch & RM=F220-00-00,F220-00-00_0009            ,2812.336
    2048    2048
River Rch & RM=F220-00-00,F220-00-00_0009            ,2426.825
    2128    2128
River Rch & RM=F220-00-00,F220-00-00_0009            ,1472.816
    2720    2720
Boundary for River Rch & Prof#=F220-00-00,F220-00-00_0009            , 1
Up Type= 0
Dn Type= 1
Dn Known WS=1.42
Boundary for River Rch & Prof#=F220-00-00,F220-00-00_0009            , 2
Up Type= 0
Dn Type= 1
Dn Known WS=2.42
DSS Import GetInterval= 0
DSS Import GetPeak= 0
DSS Import FillOption= 0

--- F220-00-00.f04 (steady flow) ---

Flow Title=FEMA Effective June 2007
Version=Version 3.0.1  Mar 2001
Number of Profiles= 4
Profile Names=10PCT_10yr, 2PCT_50yr, 1PCT_100yr, 0.2PCT_500yr
River Rch & RM=Pine Gully,Main            ,11706.55
     152     223     260     367
River Rch & RM=Pine Gully,Main            ,11638.41
     156     229     267     378
River Rch & RM=Pine Gully,Main            ,11546.71
     215     315     367     520
River Rch & RM=Pine Gully,Main            ,10515.52
     363     533     621     878
River Rch & RM=Pine Gully,Main            ,8818.841
     498     734     856    1213
River Rch & RM=Pine Gully,Main            ,6587.084
     690    1022    1193    1692
River Rch & RM=Pine Gully,Main            ,4284.019
    1169    1729    2016    2848
River Rch & RM=Pine Gully,Main            ,2812.336
    1186    1756    2048    2896
River Rch & RM=Pine Gully,Main            ,2426.825
    1229    1824    2128    3017
River Rch & RM=Pine Gully,Main            ,1472.816
    1574    2333    2720    3856
River Rch & RM=F220-00-00,F220-00-00_0009            ,11706.55
     152     223     260     367
River Rch & RM=F220-00-00,F220-00-00_0009            ,11638.41
     156     229     267     378
River Rch & RM=F220-00-00,F220-00-00_0009            ,11546.71
     215     315     367     520
River Rch & RM=F220-00-00,F220-00-00_0009            ,10515.52
     363     533     621     878
River Rch & RM=F220-00-00,F220-00-00_0009            ,8818.841
     498     734     856    1213
River Rch & RM=F220-00-00,F220-00-00_0009            ,6587.084
     690    1022    1193    1692
River Rch & RM=F220-00-00,F220-00-00_0009            ,4284.019
    1169    1729    2016    2848
River Rch & RM=F220-00-00,F220-00-00_0009            ,2812.336
    1186    1756    2048    2896
River Rch & RM=F220-00-00,F220-00-00_0009            ,2426.825
    1229    1824    2128    3017
River Rch & RM=F220-00-00,F220-00-00_0009            ,1472.816
    1574    2333    2720    3856
Boundary for River Rch & Prof#=F220-00-00,F220-00-00_0009            , 1
Up Type= 0
Dn Type= 1
Dn Known WS=1.42
Boundary for River Rch & Prof#=F220-00-00,F220-00-00_0009            , 2
Up Type= 0
Dn Type= 1
Dn Known WS=1.42
Boundary for River Rch & Prof#=F220-00-00,F220-00-00_0009            , 3
Up Type= 0
Dn Type= 1
Dn Known WS=1.42
Boundary for River Rch & Prof#=F220-00-00,F220-00-00_0009            , 4
Up Type= 0
Dn Type= 1
Dn Known WS=1.42
DSS Import GetInterval= 0
DSS Import GetPeak= 0
DSS Import FillOption= 0

--- F220-00-00.g02 (geometry) ---

Geom Title=F220-00-00 June 2007 (Floodway)
Version=Version 3.0.1  Mar 2001

River Reach=F220-00-00      ,F220-00-00_0009
Reach XY= 30
     3230379.835    13783559.944     3230706.683    13783559.626
     3231077.899    13783597.092     3232480.435    13783669.561
     3233159.612    13783132.493     3233505.093    13782900.445
     3233599.013    13782876.351     3234325.177     13782938.96
     3234624.911    13782930.086     3234908.376    13782965.088
     3235499.112    13782968.493     3236255.862    13783030.493
     3237553.606    13783084.151     3237690.073    13783122.641
      3237823.04    13783197.873     3238472.356     13783634.46
     3239140.362    13784038.493     3239230.362    13784049.493
     3239352.662    13784011.973     3239409.112    13784056.493
     3239459.569    13784147.276     3239541.419    13784186.531
     3239619.093    13784168.991     3239752.112    13784183.493
     3239948.619    13784239.635     3240060.082    13784352.737
     3240308.138    13784493.886     3240536.984    13784424.564
     3240991.362    13784115.493     3241594.612    13783600.493

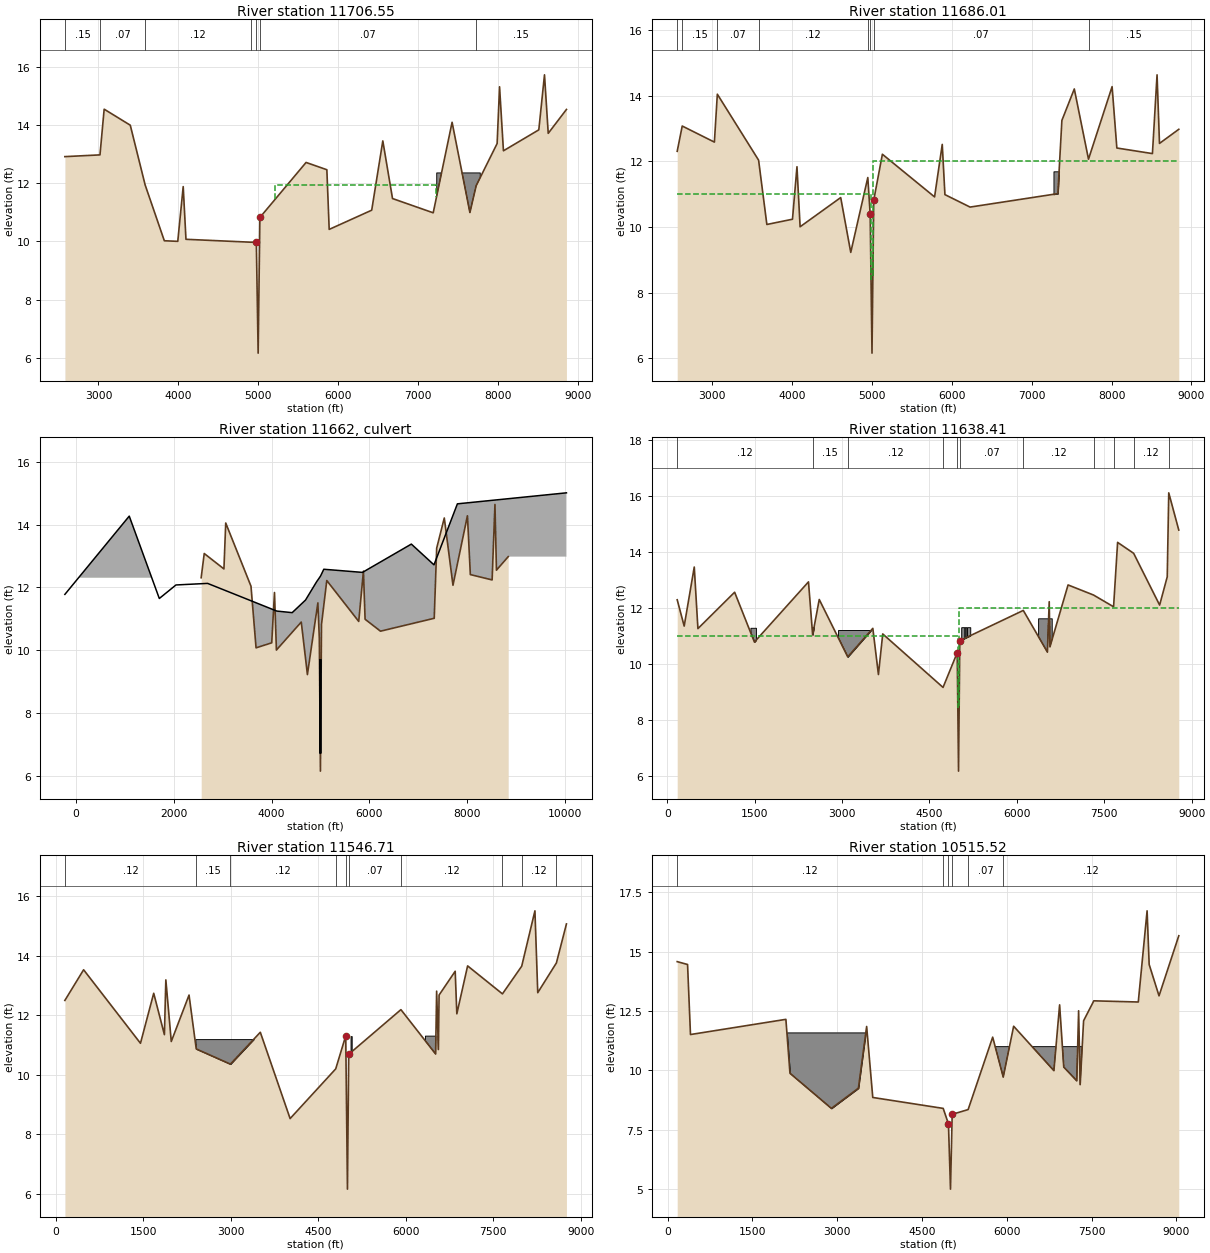
Type RM Length L Ch R = 1 ,11706.55,36.16,20.54,67.66
XS GIS Cut Line= 6
     3231046.852    13785994.376     3230987.847    13783715.725
     3230378.278    13782071.631     3230322.546    13781733.755
     3230288.737    13780870.088     3230458.772    13779846.428
#Sta/Elev= 30
 2579.11   12.91  3018.7   12.97 3071.11   14.54 3397.93   13.99 3583.89   11.94
 3824.38   10.02 3992.62      10  4060.7   11.88 4095.31   10.07 4909.85    9.97
  4976.3    9.97 4999.04    6.16  5020.9   10.82 5599.06   12.71 5859.32   12.46
 5888.53   10.41 6420.88   11.07 6559.91   13.45 6681.42   11.47 7190.88   10.98
 7427.26   14.09 7650.26   10.99  7728.6   11.91 7991.18   13.36 8021.59   15.31
 8070.22   13.11 8513.02   13.83 8584.19   15.72 8630.92   13.71 8858.98   14.53
#Mann= 7 ,-1 , 0
 2579.11     .15       0  3018.7     .07       0 3583.89     .12       0
 4909.85     .07       0  4976.3     .04       0  5020.9     .07       0
  7728.6     .15       0
#XS Ineff= 1 ,-1
    5213    7231   11.92
Permanent Ineff=
       F
#Block Obstruct= 1 ,-1
    7235    7780   12.35
Bank Sta=4976.3,5020.9
XS Rating Curve= 0
Exp/Cntr=.5,.3

Type RM Length L Ch R = 1 ,11686.01,156.18,47.6,140.2
XS GIS Cut Line= 6
     3231123.864    13786012.738     3231015.713    13783733.141
     3230472.308    13782033.357     3230317.558    13781235.914
     3230308.774    13780871.397     3230484.045    13779849.292
#Sta/Elev= 30
 2559.29   12.31 2622.11   13.08 3025.03   12.59 3061.88   14.05 3578.69   12.04
 3682.22   10.08 4003.05   10.24 4059.29   11.84 4098.56   10.01 4607.09    10.9
 4733.06    9.23  4946.6   11.51  4976.3   10.39 4999.04    6.16  5020.9   10.82
 5129.19   12.22 5782.94   10.92 5878.94   12.52  5912.6   10.99 6227.75   10.61
 7327.18   11.02 7377.52   13.25 7533.03   14.21 7710.85   12.07 8006.46   14.28
 8065.94   12.41 8511.61   12.24 8569.56   14.64    8600   12.55 8841.69   12.98
#Mann= 8 ,-1 , 0
 2559.29     .12       0 2622.11     .15       0 3061.88     .07       0
 3578.69     .12       0  4946.6     .07       0  4976.3     .04       0
  5020.9     .07       0 7710.85     .15       0
#XS Ineff= 2 , 0
       0    4987      11    5010       0      12
Permanent Ineff=
       F       F
#Block Obstruct= 2 ,-1
    7672    7810      12    7272    7352    11.7
Bank Sta=4976.3,5020.9
XS Rating Curve= 0
Exp/Cntr=.5,.3

Type RM Length L Ch R = 2 ,11662   ,,,
BEGIN DESCRIPTION:
Old Highway 146
END DESCRIPTION:
Bridge Culvert--1,0,-1,-1, 0
Deck Dist Width WeirC Skew NumUp NumDn MinLoCord MaxHiCord MaxSubmerge Is_Ogee
10,30.5,2.6,0, 16, 16, , , .95, 0, 0,0,,
    -229    1088    1703    2044    2691    4106    4421    4694    4920    5000
    5068    5859    6859    7322    7801   10032
   11.78   14.27   11.65   12.08   12.13   11.25    11.2    11.6   12.18   12.36
   12.58   12.48   13.38   12.72   14.66   15.01
                                                                                
                                                
    -229    1088    1703    2044    2691    4106    4421    4694    4920    5000
    5068    5859    6859    7322    7801   10032
   11.78   14.27   11.65   12.08   12.13   11.25    11.2    11.6   12.18   12.36
   12.58   12.48   13.38   12.72   14.66   15.01
                                                                                
                                                
BR Coef=-1 , 0 , 0 ,, 0 ,,,.8,-1,,0,
WSPro=,,,, 1 ,,,, 0 ,,,, 0 ,,,,-1 ,-1 ,-1 , 0 , 0 , 0 , 0 , 0
Multiple Barrel Culv=1,3,,46,.012,.5,1,1,1,6.72,6.72, 3,Culvert #1  , 0 ,1
  4993.6  4993.6    4999    4999  5004.4  5004.4
Culvert Bottom n=.012
BC Design=,, 0 ,, 0 ,,,,,,

Type RM Length L Ch R = 1 ,11638.41,152.27,91.7,78.68
XS GIS Cut Line= 6
     3232628.159    13788120.269     3231297.857    13784102.366
     3231010.928    13783563.073     3231029.646      13783367.4
      3230604.69    13781563.076     3230643.117    13779859.665
#Sta/Elev= 30
  171.01   12.28  290.69   11.34  463.62   13.45  526.48   11.25 1156.36   12.55
 1495.99   10.77 2423.95   12.92 2495.12   11.03 2608.66   12.29 3097.67   10.24
 3528.07   11.26 3624.26    9.61 3698.23   11.06 4733.16    9.15  4976.3   10.39
 4999.04    6.16  5020.9   10.82 6110.41    11.9 6524.49   10.41 6555.33   12.21
 6568.03    10.6 6878.67   12.81  7315.5   12.45 7659.82   12.03 7728.92   14.33
 8004.13   13.94 8450.16   12.09  8580.7    13.1 8606.68    16.1 8778.83   14.77
#Mann= 11 ,-1 , 0
  171.01     .12       0 2495.12     .15       0 3097.67     .12       0
 4733.16     .07       0  4976.3     .04       0  5020.9     .07       0
 6110.41     .12       0  7315.5     .07       0 7659.82     .15       0
 8004.13     .12       0 8606.68     .15       0
#XS Ineff= 2 , 0
       0    4987      11    5010       0      12
Permanent Ineff=
       F       F
#Block Obstruct= 7 ,-1
    2469    2524    11.3    2931    3527    11.2    5045    5098    11.3
    6373    6607    11.6    1428    1522   11.28    5106    5134    11.3
    5144    5200    11.3
Bank Sta=4976.3,5020.9
XS Rating Curve= 0
Exp/Cntr=.5,.3

Type RM Length L Ch R = 1 ,11546.71,803.52,1031.19,1049.62
XS GIS Cut Line= 6
     3232711.964     13788122.33      3231569.55     13784342.71
      3231461.57     13784064.05     3231087.955    13783541.446
     3230782.336    13781082.387     3230729.046    13779867.239
#Sta/Elev= 30
  154.74    12.5   476.1   13.53 1450.78   11.06  1677.8   12.74 1861.16   11.35
 1885.76   13.19  1978.9   11.12 2283.42   12.68 2406.78   10.87 2992.82   10.36
 3505.36   11.43 4016.22    8.53 4797.94    10.2 4969.59   11.31 4999.04    6.16
  5020.9   10.69 5915.74   12.19 6510.58    10.7  6527.9   12.81  6558.2   10.85
 6569.94   12.68 6846.04   13.48 6874.38   12.05 7059.04   13.66 7656.26   12.72
 7986.42   13.65    8213   15.51 8261.44   12.76 8581.28   13.76 8753.24   15.07
#Mann= 10 ,-1 , 0
  154.74     .12       0 2406.78     .15       0 2992.82     .12       0
 4797.94     .07       0 4969.59    .042       0  5020.9     .07       0
 5915.74     .12       0 7656.26     .15       0 7986.42     .12       0
 8581.28     .15       0
#Block Obstruct= 3 ,-1
    2392    3505    11.2    5052    5072    11.3    6336    6567    11.3
Bank Sta=4969.59,5020.9
XS Rating Curve= 0
Exp/Cntr=.3,.1

Type RM Length L Ch R = 1 ,10515.52,1727.47,1696.68,1662.53
XS GIS Cut Line= 5
     3232902.467      13788402.9     3232138.898    13784478.415
     3232135.042    13783850.762     3232133.178    13783346.559
     3232093.098    13779602.996
#Sta/Elev= 30
  168.26   14.58  351.34   14.46  402.98   11.51 2090.98   12.15 2163.16    9.88
  2896.2     8.4 3373.94    9.25  3519.7   11.85  3628.1    8.86    4874     8.4
 4966.94    7.75 5003.22       5 5033.06    8.15 5315.02    8.35 5749.52    11.4
 5936.18    9.72 6120.44   11.86 6832.34    9.99  6933.7   12.76 7006.96   10.14
 7237.38    9.56 7269.76   12.51 7297.38     9.4 7357.84   12.09 7538.88   12.93
 8325.36   12.88 8481.32   16.72 8518.04   14.46 8692.46   13.14 9041.98   15.67
#Mann= 6 ,-1 , 0
  168.26     .12       0    4874     .07       0 4966.94     .04       0
 5033.06     .12       0 5315.02     .07       0 5936.18     .12       0
#Block Obstruct= 2 ,-1
    2095    3520    11.6    5791    7350      11
Bank Sta=4966.94,5033.06
XS Rating Curve= 0
Exp/Cntr=.3,.1

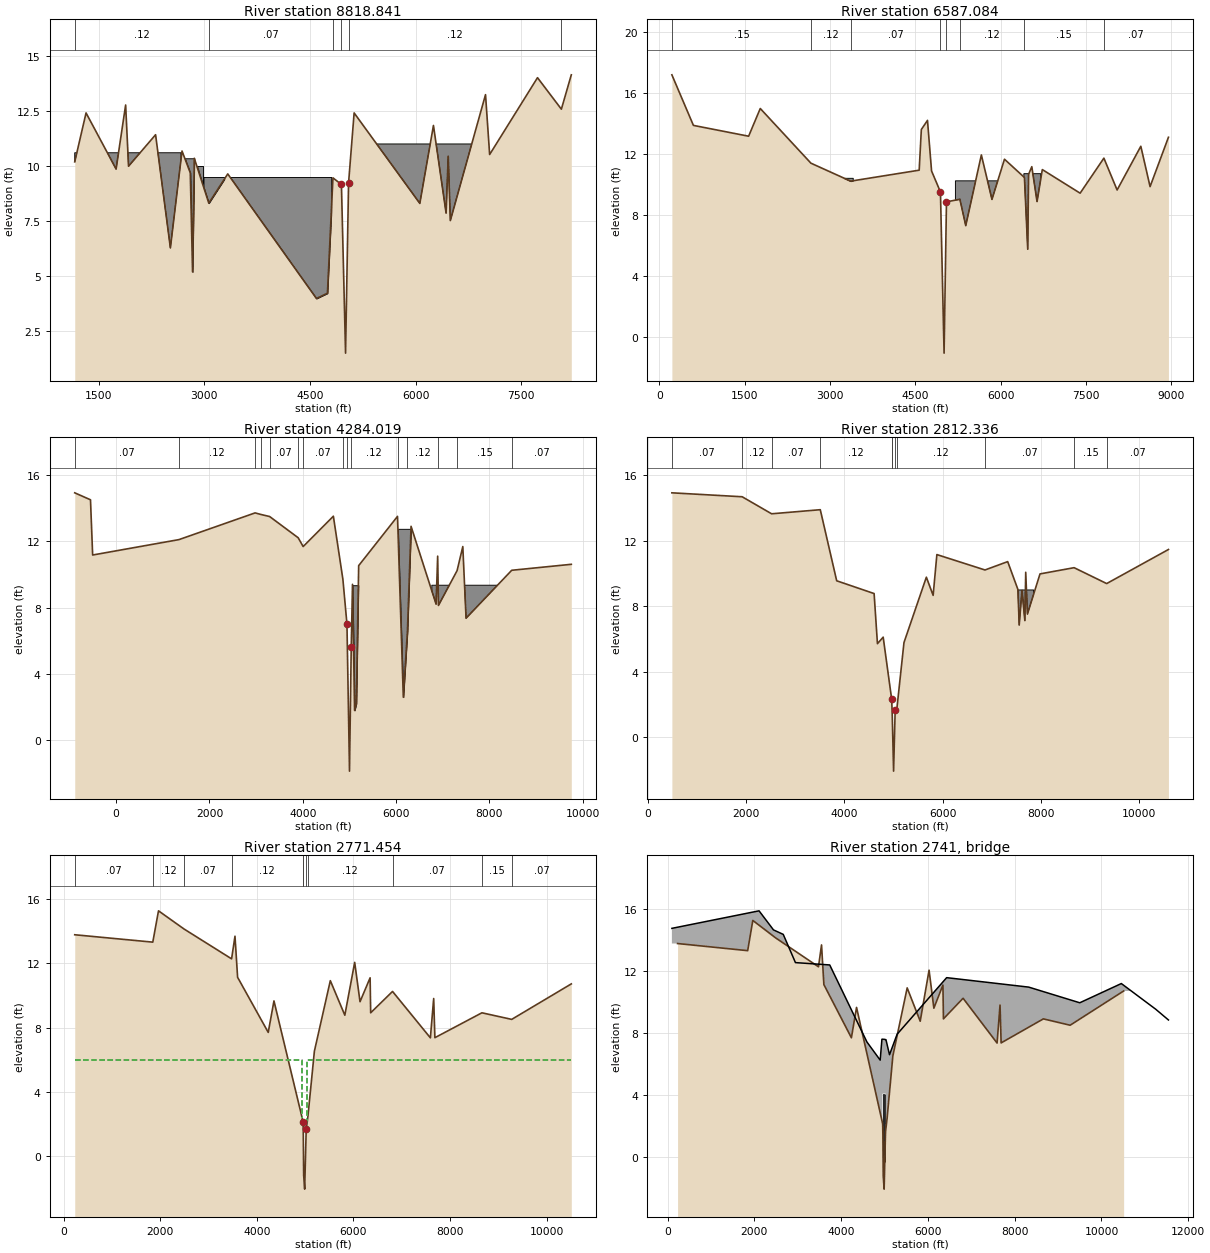
Type RM Length L Ch R = 1 ,8818.841,2170.99,2231.76,2245.39
XS GIS Cut Line= 4
     3233864.427    13786717.922     3233609.333    13783154.392
     3233532.548    13782647.612     3233254.183    13779698.361
#Sta/Elev= 30
  1162.6   10.19  1323.2   12.41 1749.49    9.86 1884.87   12.77 1926.39    9.99
    2310   11.42 2520.08    6.28 2685.12   10.68 2802.21    9.69 2834.78    5.19
 2859.47   10.35 3065.44    8.31 3334.18    9.64 4593.04    3.98 4748.89    4.22
 4827.34    9.46 4947.61    9.16 5006.22     1.5    5049    9.23 5127.85   12.41
 6060.23     8.3 6253.75   11.84 6433.17    7.86  6463.3   10.44 6493.43    7.52
 6992.67   13.24  7051.2   10.52 7730.53   14.01 8069.22   12.58 8210.17   14.14
#Mann= 6 ,-1 , 0
  1162.6     .12       0 3065.44     .07       0 4827.34     .12       0
 4947.61    .035       0    5049     .12       0 8069.22     .07       0
#Block Obstruct= 6 ,-1
  1162.6 2670.79    10.6    2681  2859.4   10.35    2860    2980      10
    2990    3284     9.5    5348    6904      11    3341  4802.3     9.5
Bank Sta=4947.61,5049
XS Rating Curve= 0
Exp/Cntr=.3,.1

Type RM Length L Ch R = 1 ,6587.084,2112.65,2303.06,2511.65
XS GIS Cut Line= 4
     3235715.601     13787771.01     3235780.539    13783220.347
     3235772.364    13782684.873     3235291.435    13779076.037
#Sta/Elev= 30
  221.75   17.21   600.3   13.89  1570.7   13.18 1775.24      15 2665.42   11.41
 3363.62   10.23 4568.17   10.95 4606.24   13.62 4714.25   14.22 4785.72    10.9
    4942    9.52 5005.89   -1.06 5047.83    8.87 5283.64    9.04 5386.71    7.31
 5661.13   11.95 5847.34    9.03 6067.29   11.67 6418.21   10.47 6476.02    5.76
 6491.15   10.68 6547.79   11.18 6639.86    8.89 6732.38   10.99 7396.93    9.44
 7814.59   11.74 8046.95    9.65 8463.71   12.52 8626.48    9.87 8949.15   13.11
#Mann= 8 ,-1 , 0
  221.75     .15       0 2665.42     .12       0 3363.62     .07       0
    4942     .04       0 5047.83     .07       0 5283.64     .12       0
 6418.21     .15       0 7814.59     .07       0
#Block Obstruct= 3 ,-1
    3247    3400   10.45    6408    6703   10.72    5205    6022   10.25
Bank Sta=4942,5047.83
XS Rating Curve= 0
Exp/Cntr=.3,.1

Type RM Length L Ch R = 1 ,4284.019,1887.96,1471.68,976.66
XS GIS Cut Line= 6
      3236388.29    13788950.445     3237556.177    13784200.848
     3237804.783    13783639.004     3237900.764    13783495.033
     3238272.057    13782909.047     3236272.372    13779129.514
#Sta/Elev= 30
 -888.44   14.92 -550.74    14.5  -504.4   11.17 1347.68    12.1  2979.5   13.71
 3097.62   13.62  3291.2   13.49 3903.24   12.21 4009.72   11.68 4657.46   13.51
 4861.58    9.71    4949       7 5003.44   -1.86 5040.65    5.61  5067.6     9.4
 5112.64     1.8  5149.6    2.21 5200.26   10.53 6032.88    13.5 6157.54     2.6
 6245.84    6.57 6323.46    12.9 6860.14    8.21 6894.08    11.1 6911.04    8.13
 7310.66   10.23 7433.12   11.68 7503.02    7.36 8481.96   10.25 9759.74   10.61
#Mann= 15 ,-1 , 0
 -888.44     .07       0 1347.68     .12       0  2979.5     .07       0
 3097.62     .12       0  3291.2     .07       0 3903.24     .12       0
 4009.72     .07       0 4861.58     .12       0    4949    .035       0
 5040.65     .12       0 6032.88     .07       0 6245.84     .12       0
 6894.08     .07       0 7310.66     .15       0 8481.96     .07       0
#Block Obstruct= 3 ,-1
    6040    6328   12.75  5067.5    5200    9.35    6769    8770    9.35
Bank Sta=4949,5040.65
XS Rating Curve= 0
Exp/Cntr=.3,.1

Type RM Length L Ch R = 1 ,2812.336,70.15,40.88,93.95
XS GIS Cut Line= 6
     3240239.049    13788307.255     3240353.818    13786561.468
     3240310.926     13786206.81     3240219.589    13785927.105
     3239217.887    13783936.107     3236542.887    13779156.086
#Sta/Elev= 30
   486.9   14.93 1917.48   14.69 2516.88   13.65  3507.7    13.9 3841.68    9.56
 4603.38    8.78  4671.2    5.72 4788.04    6.12    4961    2.33 4971.24    1.47
 5000.01   -2.06 5030.36    1.47 5033.72    1.67 5068.75    1.81 5211.44    5.79
  5666.9    9.78 5804.96    8.67 5880.88   11.16 6860.36   10.22  7322.6   10.73
  7530.5    9.03 7556.66    6.86 7613.92    8.97  7672.1    7.13 7689.48   10.08
 7724.24    7.53 7980.42    9.98 8674.16   10.36  9337.2    9.3910594.62   11.47
#Mann= 11 ,-1 , 0
   486.9     .07       0 1917.48     .12       0 2516.88     .07       0
  3507.7     .12       0    4961    .035       0 4971.24    .032       0
 5030.36    .035       0 5068.75     .12       0 6860.36     .07       0
 8674.16     .15       0  9337.2     .07       0
#Block Obstruct= 1 ,-1
    7530    7850       9
Bank Sta=4961,5033.72
XS Rating Curve= 0
Exp/Cntr=.5,.3

Type RM Length L Ch R = 1 ,2771.454,97.07,55.23,122.79
XS GIS Cut Line= 6
     3240300.664    13788546.238     3240411.196    13786562.932
     3240371.209    13786214.481     3240281.716     13785926.88
     3238982.956    13783405.269     3236690.648    13779180.291
#Sta/Elev= 30
   229.2   13.78  1845.3   13.32 1963.46   15.27 2491.22   14.14 3477.12   12.28
 3547.18   13.69 3601.42   11.13 4235.84     7.7 4354.24    9.66 4956.28    2.15
 4961.24    1.47 4969.32    -1.2 4990.01   -2.06 5020.36    1.47 5023.72    1.67
 5058.75    2.51 5191.38    6.53 5521.26   10.92  5821.8    8.77  6025.9   12.06
 6136.32    9.61 6345.22    11.1 6356.88    8.92 6809.62   10.25 7593.18    7.36
 7661.58    9.81 7686.36    7.37 8660.36    8.92 9277.28    8.51 10511.1   10.72
#Mann= 11 ,-1 , 0
   229.2     .07       0  1845.3     .12       0 2491.22     .07       0
 3477.12     .12       0 4956.28    .035       0 4961.24    .032       0
 5020.36    .035       0 5058.75     .12       0 6809.62     .07       0
 8660.36     .15       0 9277.28     .07       0
#XS Ineff= 2 , 0
       0    4941       6    5037       0       6
Permanent Ineff=
       F       F
Bank Sta=4956.28,5023.72
XS Rating Curve= 0
Exp/Cntr=.5,.3

Type RM Length L Ch R = 3 ,2741    ,,,
Bridge Culvert--1,0,-1,-1, 0
Deck Dist Width WeirC Skew NumUp NumDn MinLoCord MaxHiCord MaxSubmerge Is_Ogee
10,35,2.6,0, 21, 21, , , .95, 0, 0,0,,
      98    2107    2440    2665    2946    3736    4594    4899    4939    4951
    5000    5027    5032    5114    5289    6431    8322    9499   10457   11251
   11543
   14.76   15.89   14.66   14.37   12.55    12.4    7.43    6.26    7.61    7.61
     7.6    7.58    7.58    6.61    7.93   11.58   10.97    9.96    11.2    9.54
    8.85
                                                                             4.1
     4.1     4.1
        
      98    2107    2440    2665    2946    3736    4594    4899    4939    4951
    5000    5027    5032    5114    5289    6431    8322    9499   10457   11251
   11543
   14.76   15.89   14.66   14.37   12.55    12.4    7.43    6.26    7.61    7.61
     7.6    7.58    7.58    6.61    7.93   11.58   10.97    9.96    11.2    9.54
    8.85
                                                                             4.1
     4.1     4.1
        
Pier Skew, UpSta & Num, DnSta & Num=  ,4975, 4 ,4975, 4 , 3 , 3 , 0 ,,
     1.3     1.3       2       2
      -3    2.08    2.08     4.5
     1.3     1.3       2       2
      -3    2.08    2.08     4.5
Pier Skew, UpSta & Num, DnSta & Num=  ,5005, 4 ,5005, 4 , 3 , 3 , 0 ,,
     1.3     1.3       2       2
      -3    2.08    2.08     4.5
     1.3     1.3       2       2
      -3    2.08    2.08     4.5
BR Coef=-1 , 1 , 1 ,1.25, 0 ,,,.8,0,2,0,
WSPro=,,,, 1 ,,,, 0 ,,,, 0 ,,,,-1 ,-1 ,-1 , 0 , 0 , 0 , 0 , 0
BC Design=,, 0 ,, 0 ,,,,,,

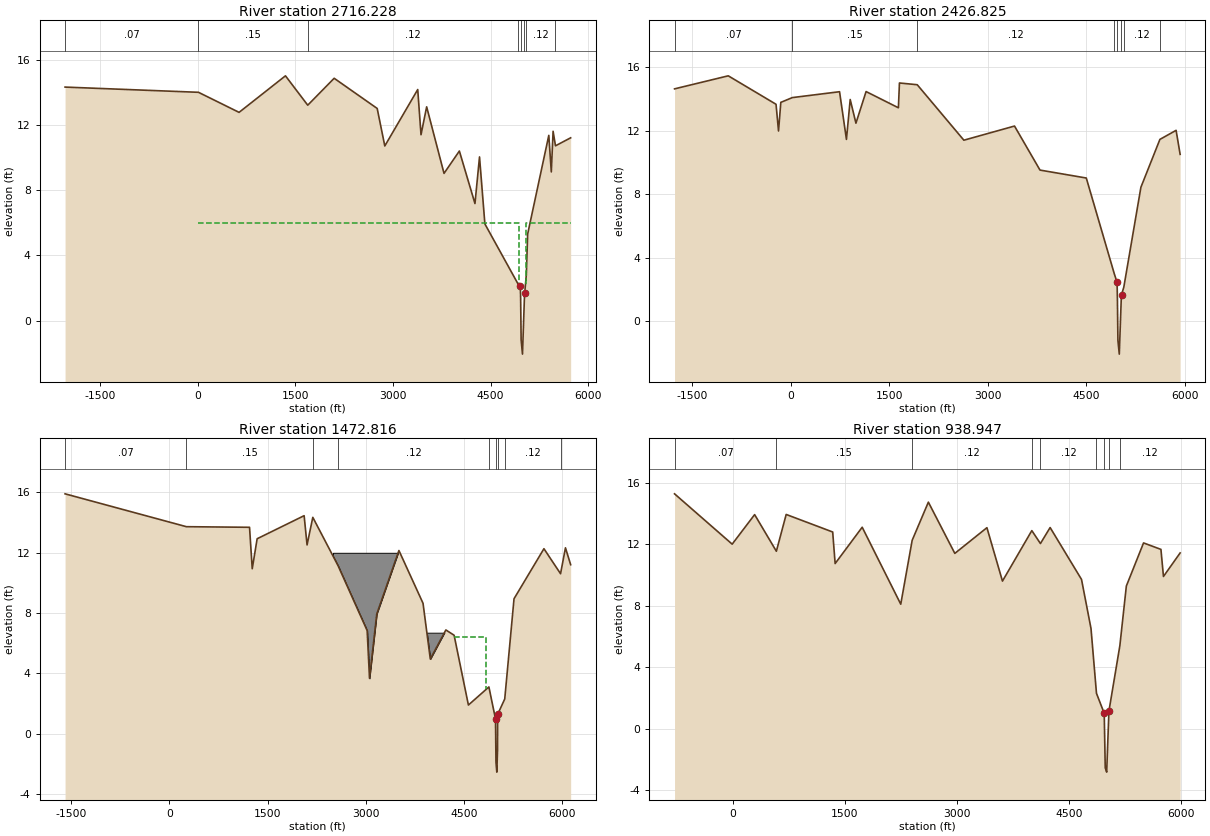
Type RM Length L Ch R = 1 ,2716.228,173.18,289.4,148.67
XS GIS Cut Line= 6
     3241879.358    13790558.596     3241066.766    13787888.152
     3240673.864    13786667.774     3240196.338    13785591.977
     3239371.902    13784038.846     3239035.717    13783355.523
#Sta/Elev= 30
 -2040.8   14.31    9.65   13.99   633.9   12.76  1346.8      15 1689.42    13.2
 2095.35   14.85 2756.73      13 2873.71    10.7 3379.88   14.16 3430.29   11.39
  3517.1    13.1 3784.03    9.02 4019.91   10.39 4259.64    7.17 4329.48   10.03
 4412.18    5.92 4917.67    2.27 4956.28    2.09 4961.24    1.47 4969.32    -1.2
 4990.01   -2.06 5020.36    1.47 5023.72    1.67    5049     2.8 5069.53     5.3
 5394.44   11.35 5432.94    9.11 5460.61    11.6 5497.36   10.71  5730.5    11.2
#Mann= 8 ,-1 , 0
 -2040.8     .07       0    9.65     .15       0 1689.42     .12       0
 4917.67    .035       0 4961.24    .032       0 5020.36    .035       0
    5049     .12       0 5497.36     .07       0
#XS Ineff= 2 , 0
       0    4941       6    5037       0       6
Permanent Ineff=
       F       F
Bank Sta=4956.28,5023.72
XS Rating Curve= 0
Exp/Cntr=.5,.3

Type RM Length L Ch R = 1 ,2426.825,792.35,954.01,1000.21
XS GIS Cut Line= 6
     3241967.478     13790479.22     3240767.654    13786632.785
     3240451.724    13785889.253      3240285.77    13785547.217
      3239461.03    13783993.363     3239141.336    13783347.353
#Sta/Elev= 30
 -1766.5   14.63 -948.57   15.45 -221.17   13.66 -183.31   11.98 -148.42   13.78
   26.47   14.08  745.83   14.45  850.85   11.45  908.05   13.96  995.33   12.47
 1149.78   14.46 1641.87   13.44 1657.89      15 1928.52   14.89 2638.67    11.4
 3409.73   12.29 3797.83    9.52 4502.63    9.02 4931.53    2.96 4971.28    2.46
 4976.24    1.47 4984.32    -1.2 5005.01   -2.06 5035.36    1.47 5038.72    1.67
 5073.75    2.15 5334.33    8.44 5623.54   11.45 5869.99   12.02 5931.46   10.51
#Mann= 8 ,-1 , 0
 -1766.5     .07       0   26.47     .15       0 1928.52     .12       0
 4931.53    .035       0 4976.24    .032       0 5035.36    .035       0
 5073.75     .12       0 5623.54     .07       0
Bank Sta=4971.28,5038.72
XS Rating Curve= 0
Exp/Cntr=.3,.1

Type RM Length L Ch R = 1 ,1472.816,613.06,533.87,443.95
XS GIS Cut Line= 4
     3242557.387    13790712.335     3241941.809    13788919.847
      3240077.09    13783479.681     3240050.235    13783405.906
#Sta/Elev= 30
-1592.97   15.91  260.94   13.73 1225.36   13.69 1266.73   10.94 1341.69   12.93
 2059.41   14.46 2104.31   12.52  2192.1   14.35 2578.33   11.14 3022.36    6.84
 3058.54    3.67 3169.53    7.94 3507.84   12.15 3876.11    8.65 3987.49    4.95
 4224.97    6.88 4350.99    6.53 4569.44     1.9  4882.5     3.1 4983.65     .97
 4990.45   -1.88 5003.45   -2.55 5014.13   -1.12 5016.35    1.28 5124.42     2.3
 5266.35    8.95 5723.42   12.27 5977.17   10.61 6052.22   12.33 6131.66   11.21
#Mann= 9 ,-1 , 0
-1592.97     .07       0  260.94     .15       0  2192.1     .07       0
 2578.33     .12       0  4882.5    .035       0 4983.65    .032       0
 5016.35    .035       0 5124.42     .12       0 5977.17     .07       0
#XS Ineff= 1 ,-1
    4345    4840     6.4
Permanent Ineff=
       F
#Block Obstruct= 2 ,-1
    2500    3500      12    3900    4225     6.7
Bank Sta=4983.65,5016.35
XS Rating Curve= 0
Exp/Cntr=.3,.1

Type RM Length L Ch R = 1 ,938.947 ,1123.97,1090.24,1054.82
XS GIS Cut Line= 5
     3243945.265    13789090.019     3243388.366     13788250.64
     3240684.622    13783896.524     3240586.127    13783843.084
     3240348.878    13783387.411
#Sta/Elev= 30
 -775.06   15.27   -4.74      12  295.54   13.92  586.08   11.54  717.28   13.93
 1338.98   12.79 1371.64   10.74 1733.32    13.1 2248.82     8.1  2401.4   12.25
 2617.94   14.73 2971.54    11.4 3400.62   13.07 3608.38     9.6  4000.8   12.88
  4115.9   12.04  4245.5   13.08 4665.04    9.71 4791.96    6.52 4865.04    2.31
 4968.59    1.01 4982.27   -2.53 5001.43   -2.81 5031.41    1.15 5177.54     5.4
 5264.44    9.28 5494.24   12.08  5726.7   11.66 5760.48     9.9 5983.34   11.43
#Mann= 9 ,-1 , 0
 -775.06     .07       0  586.08     .15       0  2401.4     .12       0
  4000.8     .07       0  4115.9     .12       0 4865.04    .035       0
 4968.59    .032       0 5031.41    .035       0 5177.54     .12       0
Bank Sta=4968.59,5031.41
XS Rating Curve= 0
Exp/Cntr=.3,.1

Chan Stop Cuts=-1

--- F220-00-00.g01 (geometry) ---

Geom Title=F220-00-00 June 2007
Version=Version 3.0.1  Mar 2001

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
River Reach=F220-00-00      ,F220-00-00_0009